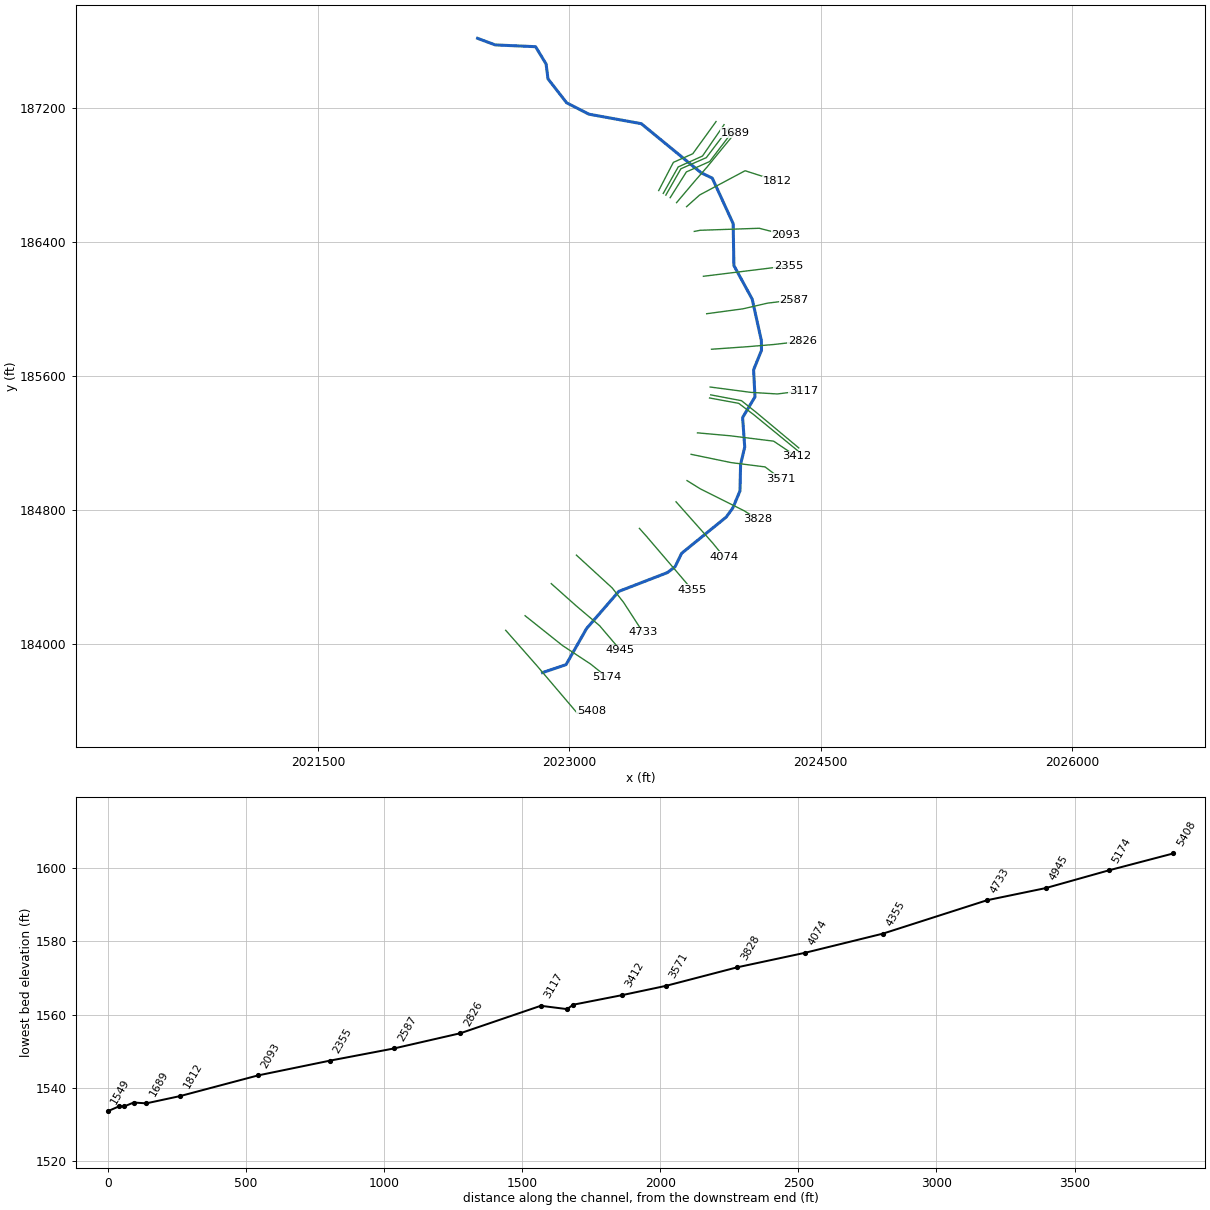
--- STNKLKCK_AE.prj (project) ---

Proj Title=STNKLKCK_AE
Current Plan=p01
Default Exp/Contr=0,0
English Units
Geom File=g01
Flow File=f01
Plan File=p01
Background Map Layer=Inundation Boundary (0_2pct Value_0)
BEGIN DESCRIPTION:
Stream Name: Stinking Lick Creek
Flood Zone: Detailed
Summers County, West Virginia
HEC-RAS Version: 5.0.7
Hydrology Method:
Regression.
Model Notes:
END DESCRIPTION:
DSS File=dss
DSS Export Rating Curves= 0
DSS Export Rating Curve Sorted= 0
DSS Export Volume Flow Curves= 0
DXF OffsetX= 0
DXF OffsetY= 0
DXF ScaleX= 0
DXF ScaleY= 0

--- STNKLKCK_AE.p01 (plan) ---

Plan Title=Floodplain
Program Version=5.07
Short Identifier=Floodplain
Geom File=g01
Flow File=f01
Subcritical Flow
K Sum by GR= 0
Std Step Tol= 0.01
Critical Tol= 0.01
Num of Std Step Trials= 20
Max Error Tol= 0.3
Flow Tol Ratio= 0.001
Split Flow NTrial= 30
Split Flow Tol= 0.02
Split Flow Ratio= 0.02
Log Output Level= 0
Friction Slope Method= 1
Unsteady Friction Slope Method= 2
Unsteady Bridges Friction Slope Method= 1
Parabolic Critical Depth
Global Vel Dist= 0 , 0 , 0
Global Log Level= 0
CheckData=True
Encroach Param=-1 ,0,0, 2
Encroach River=STNKLKCK_AE
Encroach Reach=Main
Encroach Node=5408
       1     327   374.9
Encroach Node=5174
       1  312.45   382.6
Encroach Node=4945
       1     316     346
Encroach Node=4733
       1  292.59   348.9
Encroach Node=4355
       1     280     326
Encroach Node=4074
       1     220   271.9
Encroach Node=3828
       1     280     332
Encroach Node=3571
       1  232.93     316
Encroach Node=3412
       1  214.78   301.4
Encroach Node=3234
       1     214     285
Encroach Node=3212
       1     218     285
Encroach Node=3117
       1     210     295
Encroach Node=2826
       1     262     308
Encroach Node=2587
       1     265   294.3
Encroach Node=2355
       1   187.3  241.74
Encroach Node=2093
       1   209.6  279.72
Encroach Node=1812
       1  196.79     241
Encroach Node=1689
       1   216.3  266.23
Encroach Node=1643
       1     242  295.05
Encroach Node=1610
       1   249.3  298.93
Encroach Node=1590
       1     251  300.48
Encroach Node=1549
       1     245     306
Encroach Node=1488
       1   254.3  309.69
Encroach Node=1420
       1   250.7  315.41
Encroach Node=1184
       1  263.66     306
Encroach Node=994
       1     200   235.5
Encroach Node=732
       1     153     190
Encroach Node=461
       1  234.08   279.5
Encroach Node=167
       1  163.04  201.19
Encroach Node=0
       1     133  165.16
Computation Interval=0.1SEC
Output Interval=1MIN
Instantaneous Interval=Max Profile
Mapping Interval=1HOUR
Computation Time Step Use Courant=        0
Computation Time Step Use Time Series=    0
Computation Time Step Count To Double=0
Computation Time Step Max Doubling=0
Computation Time Step Max Halving=0
Computation Time Step Residence Courant=0
Run HTab= 0
Run UNet= 0
Run Sediment= 0
Run PostProcess= 0
Run WQNet= 0
Run RASMapper= 0
UNET Theta= 0
UNET Theta Warmup= 0
UNET ZTol= 0
UNET ZSATol= 0
UNET MxIter= 0
UNET Max Iter WO Improvement= 0
UNET MaxInSteps= 0
UNET DtIC= 0
UNET DtMin= 0
UNET MaxCRTS= 0
UNET WFStab= 0
UNET SFStab= 0
UNET WFX= 1
UNET SFX= 1
UNET 1D Methodology=Finite Difference
UNET DSS MLevel= 1
UNET Pardiso=0
UNET DZMax Abort= 0
UNET Use Existing IB Tables= 0
UNET Froude Reduction=False
UNET Froude Limit= 0
UNET Froude Power= 0
UNET D1 Cores= 0
UNET D2 Coriolis=0
UNET D2 Cores= 0
UNET D2 Theta= 1
UNET D2 Theta Warmup= 1
UNET D2 Z Tol= 0.01
UNET D2 Volume Tol= 0.01
UNET D2 Max Iterations= 20
UNET D2 Equation= 0
UNET D2 RampUpFraction=0.1
UNET D2 TimeSlices= 1
UNET D2 BCVolumeCheck=0
UNET D1D2 MaxIter= 0
UNET D1D2 ZTol=0.01
UNET D1D2 QTol=0.1
UNET D1D2 MinQTol=1
DSS File=dss
Write IC File= 0
Write IC File at Fixed DateTime=0
Write IC File at Sim End=0
Echo Input=False
Echo Parameters=False
Echo Output=False
Write Detailed= 0
HDF Write Warmup=0
HDF Write Time Slices=0
HDF Flush=0
HDF Face Node Velocities=0
HDF Compression= 1
HDF Chunk Size= 1
HDF Spatial Parts= 1
HDF Use Max Rows=0
HDF Fixed Rows= 1
Calibration Method= 0
Calibration Iterations= 20
Calibration Max Change=0.05
Calibration Tolerance=0.2
Calibration Maximum=1.5
Calibration Minimum=0.5
Calibration Optimization Method= 1
WQ AD Non Conservative
WQ ULTIMATE=-1
WQ Max Comp Step=1HOUR
WQ Output Interval=15MIN
WQ Output Selected Increments= 0
WQ Output face flow=0
WQ Output face velocity=0
WQ Output face area=0
WQ Output face dispersion=0
WQ Output cell volume=0
WQ Output cell surface area=0
WQ Output cell continuity=0
WQ Output cumulative cell continuity=0
WQ Output face conc=0
WQ Output face dconc_dx=0
WQ Output face courant=0
WQ Output face peclet=0
WQ Output face adv mass=0
WQ Output face disp mass=0
WQ Output cell mass=0
WQ Output cell source sink temp=0
WQ Output nsm pathways=0
WQ Output nsm derived pathways=0
WQ Output MaxMinRange=-1
WQ Daily Max Min Mean=-1
WQ Daily Range=0
WQ Daily Time=0
WQ Create Restart=0
WQ Fixed Restart=0
WQ System Summary=0
WQ Write To DSS=0
WQ Use Fixed Temperature=0
Sorting and Armoring Iterations= 10
XS Update Threshold= 0.02
Bed Roughness Predictor= 0
Hydraulics Update Threshold= 0.02
Energy Slope Method= 1
Volume Change Method= 1
Sediment Retention Method= 0
XS Weighting Method= 0
Number of US Weighted Cross Sections= 1
Number of DS Weighted Cross Sections= 1
Upstream XS Weight=0
Main XS Weight=1
Downstream XS Weight=0
Number of DS XS's Weighted with US Boundary= 1
Upstream Boundary Weight= 1
Weight of XSs Associated with US Boundary= 0
Number of US XS's Weighted with DS Boundary= 1
Downstream Boundary Weight= 0.5
Weight of XSs Associated with DS Boundary= 0.5
Percentile Method= 0
Sediment Output Level= 3
Mass or Volume Output= 0
Output Increment Type= 1
Profile and TS Output Increment= 1
XS Output Flag= 0
XS Output Increment= 10
Write Gradation File= 0
Read Gradation Hotstart= 0
Write HDF5 File= 1
Write Binary Output= 1
Write DSS Sediment File= 0
SV Curve= 0
Specific Gage Flag= 0

--- STNKLKCK_AE.f01 (steady flow) ---

Flow Title=Flows
Program Version=5.07
Number of Profiles= 7
Profile Names=01pct,FW,10pct,04pct,02pct,0_2pct,01plus
River Rch & RM=STNKLKCK_AE,Main            ,5408
    1319    1319     720     943    1125    1814    1951
River Rch & RM=STNKLKCK_AE,Main            ,1689
    1744    1744     962    1253    1491    2386    2580
River Rch & RM=STNKLKCK_AE,Main            ,0
    1835    1835    1015    1320    1570    2508    2714
Boundary for River Rch & Prof#=STNKLKCK_AE,Main            , 1
Up Type= 0
Dn Type= 1
Dn Known WS=1521.8
Boundary for River Rch & Prof#=STNKLKCK_AE,Main            , 2
Up Type= 0
Dn Type= 1
Dn Known WS=1521.8
Boundary for River Rch & Prof#=STNKLKCK_AE,Main            , 3
Up Type= 0
Dn Type= 1
Dn Known WS=1520.1
Boundary for River Rch & Prof#=STNKLKCK_AE,Main            , 4
Up Type= 0
Dn Type= 1
Dn Known WS=1520.8
Boundary for River Rch & Prof#=STNKLKCK_AE,Main            , 5
Up Type= 0
Dn Type= 1
Dn Known WS=1521.3
Boundary for River Rch & Prof#=STNKLKCK_AE,Main            , 6
Up Type= 0
Dn Type= 1
Dn Known WS=1522.9
Boundary for River Rch & Prof#=STNKLKCK_AE,Main            , 7
Up Type= 0
Dn Type= 1
Dn Known WS=1523.2
DSS Import GetInterval= 0
DSS Import GetPeak= 0
DSS Import FillOption= 0

--- STNKLKCK_AE.g01 (geometry) ---

Geom Title=Geometry
Program Version=5.07

River Reach=STNKLKCK_AE     ,Main
Reach XY= 30
     2022839.783183827.4470000032022980.26600001 183874.91100002
2023102.95900003184090.699000006      2023295.13184312.122999998
2023585.05699999184424.1779999862023630.89000001184459.074000002
2023669.95300002184539.2830000482023936.03145762184755.431787751
2023975.16100001184809.0739999912024018.39000001184911.678000055
     2024022.036185069.4910000492024046.66700001185173.747000035
     2024034.015185349.700000034     2024107.853185473.345000027
      2024099.64185634.5950000132024146.76399999185750.802000023
2024146.12200001185808.518000018     2024091.307186056.470000038
     2023982.091186256.8640000112023977.63500002186507.187999977
     2023852.939186778.6920000012023786.27200002186810.637000043
2023429.38199999187103.6020000112023116.61199999187160.343999992
  2022983.774233187228.2114716592022872.54664513187371.117802918
     2022861.168187459.6639999972022798.47799999187563.126000011
2022557.44900003187573.7270000512022452.32795371187612.982494668

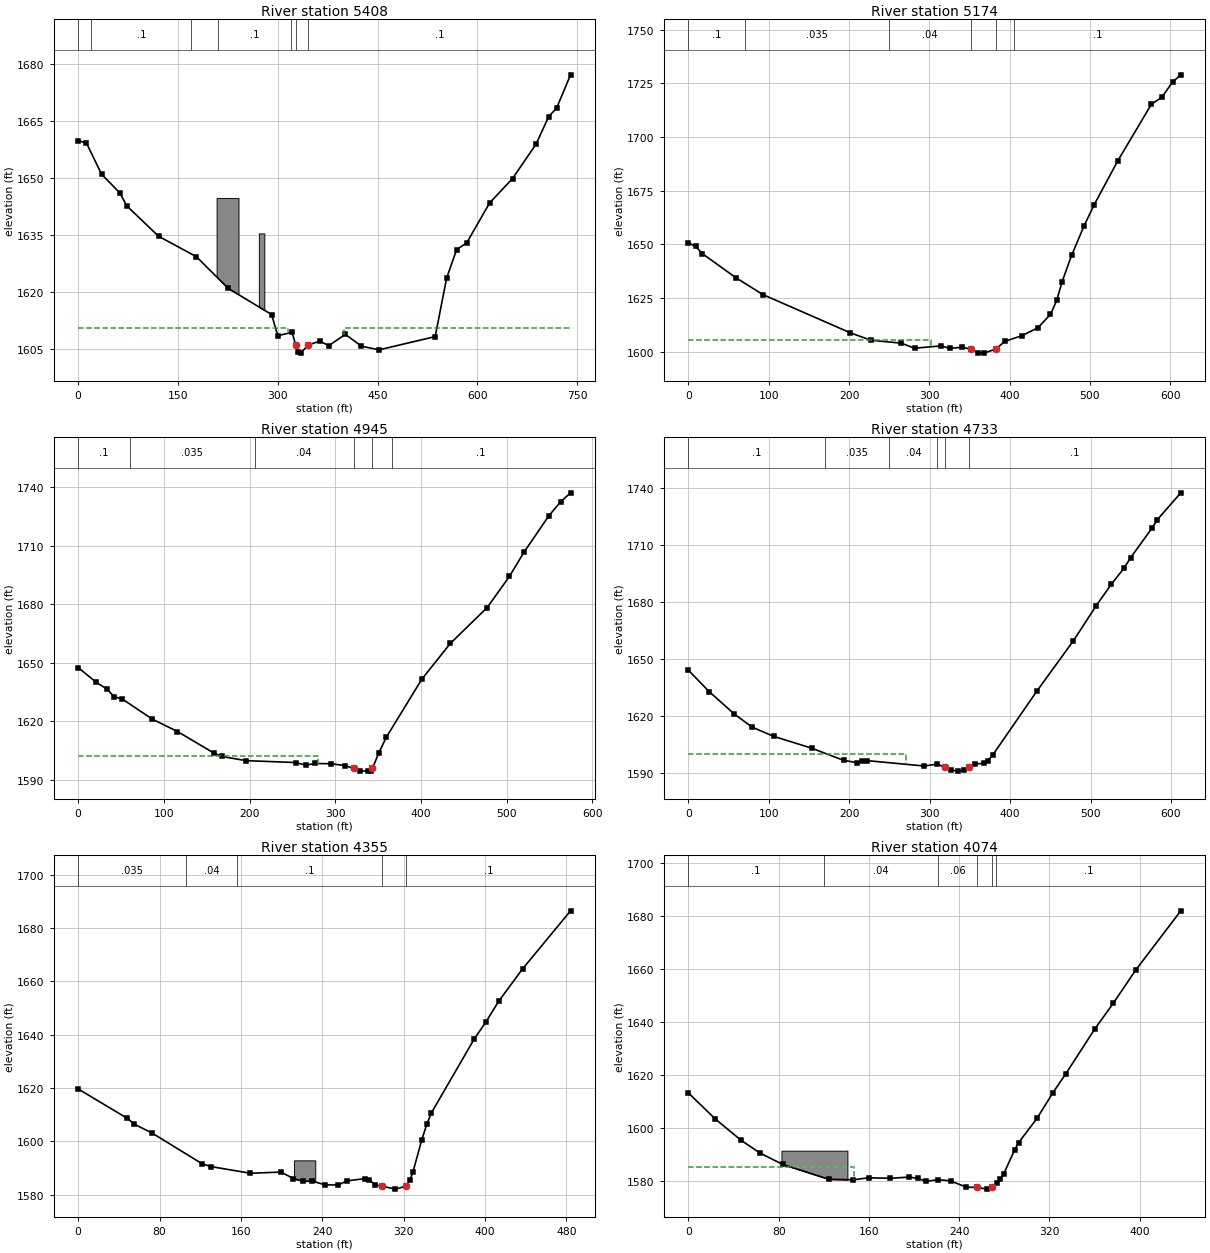
Type RM Length L Ch R = 1 ,5408    ,214.9,234.2,229.1
XS GIS Cut Line= 4
      2022619.99      184080.017     2022805.061      183870.101
     2023048.288      183584.058     2023132.211      183596.481
#Sta/Elev= 30
       0 1659.74    12.3 1659.26    35.1 1650.98      63    1646    72.7 1642.71
   120.8 1634.65   177.7 1629.27   225.6 1620.92   290.8 1614.04   300.1 1608.47
   321.4 1609.36     3271606.099     330 1604.28   334.3 1603.88     346 1606.04
     363 1607.01   376.9 1605.87   401.7 1608.82   425.8 1605.71   452.4 1604.75
   536.7 1608.23   553.9 1623.62   568.9 1631.11   584.1 1632.91   618.5  1643.4
     653 1649.84   688.3 1658.87   707.4 1666.16   719.1 1668.33   740.2 1677.13
#Mann= 7 ,-1 , 0
       0    .035       0      20      .1       0     170    .035       0
     210      .1       0  319.85     .04       0     327    .045       0
     346      .1       0
#XS Ineff= 2 , 0
           315.2 1610.56  400.26         1610.58
Permanent Ineff=
       F       F
#Block Obstruct= 2 ,-1
  208.11  241.04 1644.73  271.62  279.85 1635.39
Bank Sta=327,346
XS Rating Curve= 0 ,0
Exp/Cntr=0.3,0.1

Type RM Length L Ch R = 1 ,5174    ,230.8,228.5,226.1
XS GIS Cut Line= 4
     2022735.809      184166.822     2022959.125       183988.96
     2023127.106       183878.29     2023225.919       183799.24
#Sta/Elev= 30
       0 1650.59     9.1 1648.96    17.5 1645.57    59.5 1634.29      93 1626.49
   201.4 1608.76   227.2 1605.27     265  1603.9   281.7 1601.54   314.5 1602.64
   325.2  1601.5   340.9 1601.96   352.11601.143   360.6 1599.43   368.2 1599.26
   382.61601.155   394.4 1604.79   415.6 1607.42   435.2 1611.09   450.9 1617.29
   458.8 1623.94   465.4 1632.57   477.3 1644.87   492.6 1658.44   505.4 1668.44
   534.6 1688.76   576.7 1715.27   589.5 1718.39   602.9 1725.53   613.2 1728.91
#Mann= 6 ,-1 , 0
       0      .1       0      70    .035       0     250     .04       0
   352.1    .045       0   382.6     .04       0  405.49      .1       0
#XS Ineff= 2 , 0
           301.5 1605.52
Permanent Ineff=
       F       F
Bank Sta=352.1,382.6
XS Rating Curve= 0 ,0
Exp/Cntr=0.3,0.1

Type RM Length L Ch R = 1 ,4945    ,216.4,212,207.6
XS GIS Cut Line= 4
     2022891.933      184358.519     2023038.175      184228.086
     2023180.465      184107.535     2023304.969      183961.293
#Sta/Elev= 30
       0 1647.52    21.1 1639.91    33.4 1636.53    42.1 1632.54    51.4  1631.4
    86.1 1621.17   115.9 1614.72   158.2 1603.72   167.5 1601.95     196  1599.8
   253.6 1598.84   265.3 1597.56   276.9 1598.34   295.5 1598.22   311.5 1597.24
   321.6 1595.82   329.3 1594.51   337.9 1594.43   342.1 1594.65  343.36 1595.81
   350.8 1603.83   359.4 1611.67   400.9  1641.5   434.2 1659.85   477.1  1678.2
   503.2  1694.2   520.4 1706.78   549.2 1725.25   562.8 1732.39   574.5 1737.03
#Mann= 6 ,-1 , 0
       0      .1       0      60    .035       0  205.96     .04       0
   321.6    .045       0  343.36    .035       0  365.96      .1       0
#XS Ineff= 2 , 0
             280    1602
Permanent Ineff=
       F       F
Bank Sta=321.6,343.36
XS Rating Curve= 0 ,0
Exp/Cntr=0.3,0.1

Type RM Length L Ch R = 1 ,4733    ,375.8,377.6,370.9
XS GIS Cut Line= 4
     2023042.128      184528.476     2023255.563      184332.827
     2023322.755      184247.849     2023439.354       184068.01
#Sta/Elev= 30
       0 1644.16    25.9 1632.87      57 1621.15    79.3 1614.22     106  1609.4
   153.5 1603.15     193 1596.79   209.3 1595.61   216.2 1596.65   221.7 1596.67
   292.9 1593.83   309.2 1594.78   319.3 1593.17   325.9 1591.74   334.9 1591.13
   342.6 1591.52   348.91593.201     356 1594.89   367.7 1595.23   371.9 1596.44
   378.2 1599.46   433.6 1633.39   478.7 1659.64   507.1  1678.1     526 1689.39
   541.7 1697.84   549.8 1703.26   576.9 1719.11     583 1723.23   612.2 1737.34
#Mann= 6 ,-1 , 0
       0      .1       0     170    .035       0     250     .04       0
  309.54      .1       0   319.3    .045       0   348.9      .1       0
#XS Ineff= 2 , 0
             270    1600
Permanent Ineff=
       F       F
Bank Sta=319.3,348.9
XS Rating Curve= 0 ,0
Exp/Cntr=0.3,0.1

Type RM Length L Ch R = 1 ,4355    ,279.6,281,279
XS GIS Cut Line= 3
     2023418.211      184688.194     2023462.075      184638.809
2023733.73175677184321.054391227
#Sta/Elev= 30
       0 1619.59    48.3 1608.57    55.2 1606.37    72.5 1603.09   121.9 1591.52
   130.6 1590.47   169.4 1587.97   199.6 1588.42   211.5 1585.98   221.2 1584.95
   229.8 1585.07   242.8 1583.62   255.7 1583.58   264.4 1585.13   281.9 1585.96
     286 1585.54   292.3 1583.58     2991583.108   311.9 1582.02   322.71583.182
   326.1 1585.33   329.1 1588.36   337.7 1600.36   342.8 1606.36     347 1610.42
   389.5 1638.41   400.6 1644.53   413.5 1652.52     437 1664.65   484.1 1686.39
#Mann= 5 ,-1 , 0
       0    .035       0  106.05     .04       0  156.05      .1       0
     299    .045       0   322.7      .1       0
#Block Obstruct= 1 ,-1
  212.14  233.13 1592.81
Bank Sta=299,322.7
XS Rating Curve= 0 ,0
Exp/Cntr=0.3,0.1

Type RM Length L Ch R = 1 ,4074    ,221.2,245.9,252.1
XS GIS Cut Line= 4
     2023636.677      184846.931     2023764.738      184702.863
     2023855.982      184600.4142023922.98469651184517.694264326
#Sta/Elev= 30
       0 1613.12    23.6 1603.37    46.4 1595.34    63.1 1590.52    83.6 1586.13
   124.6 1580.53   146.1 1580.34   159.7 1581.09   178.9 1580.91   195.5 1581.35
   203.6 1580.87   210.3 1579.76   221.2 1580.36   232.3 1579.95   246.3 1577.56
   255.6 1577.47   264.9 1576.82   269.5 1577.53   273.9 1579.04   276.5 1580.47
   279.4 1582.53   289.2 1591.68   292.7 1594.39     309 1603.53   322.9 1613.09
   334.6  1620.4   360.2 1637.25   376.6 1646.94   396.4 1659.43   436.4 1681.79
#Mann= 6 ,-1 , 0
       0      .1       0     120     .04       0   221.2     .06       0
   255.6    .045       0   269.5     .06       0  272.76      .1       0
#XS Ineff= 2 , 0
           146.6 1585.01
Permanent Ineff=
       F       F
#Block Obstruct= 1 ,-1
   82.46  140.931591.324
Bank Sta=255.6,269.5
XS Rating Curve= 0 ,0
Exp/Cntr=0.3,0.1

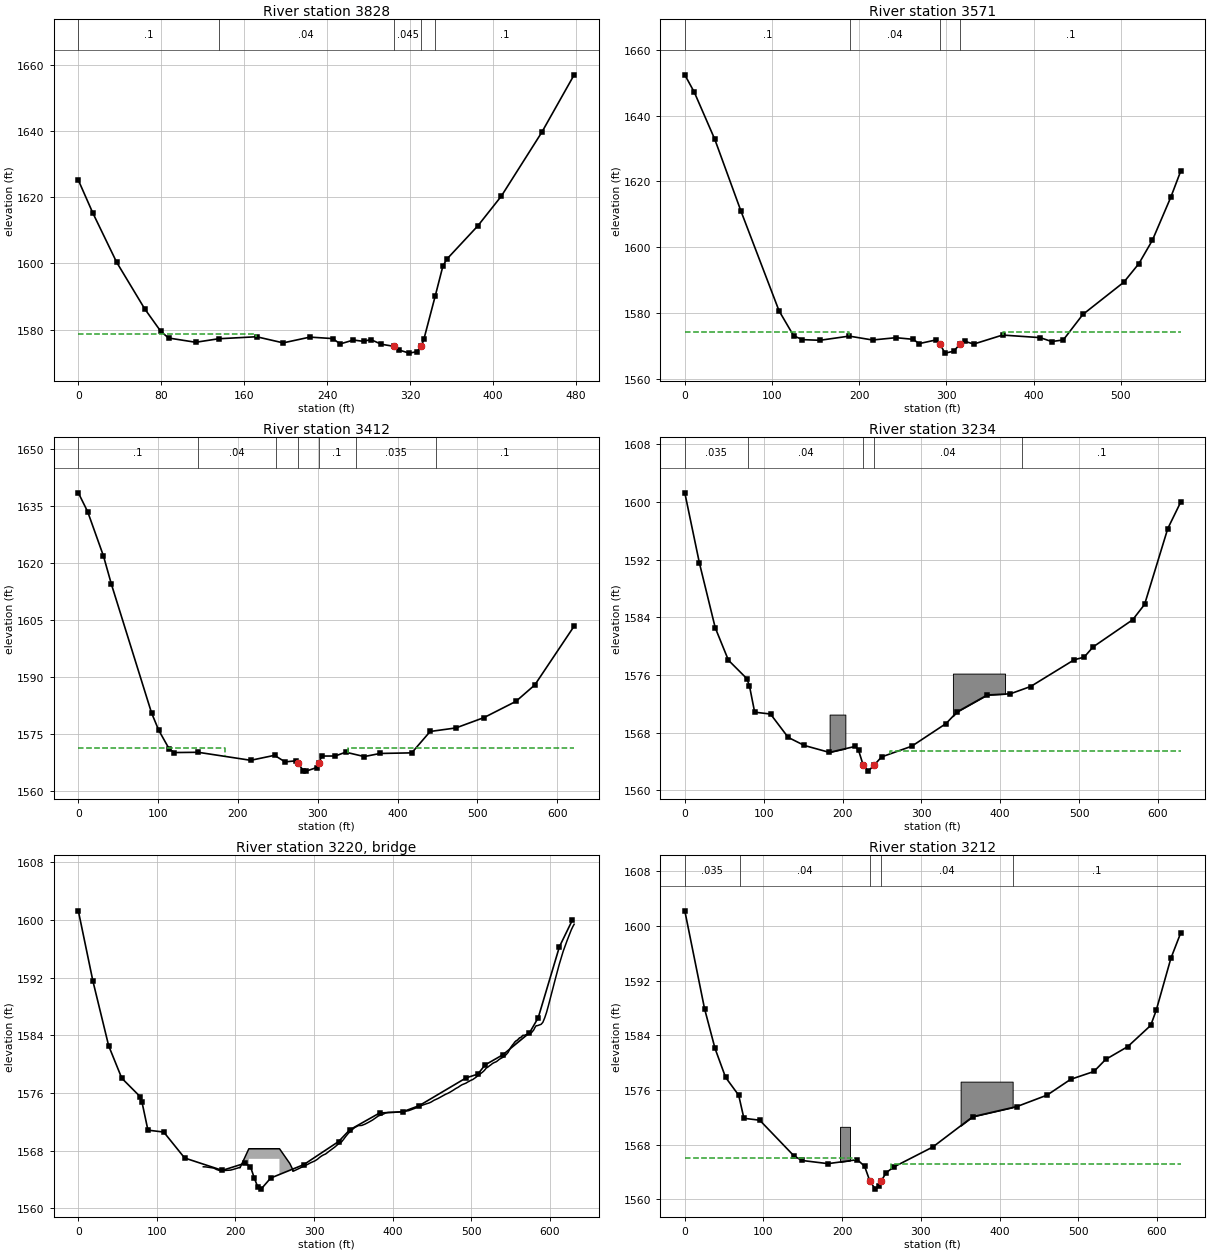
Type RM Length L Ch R = 1 ,3828    ,238.6,257.4,263
XS GIS Cut Line= 4
     2023702.309      184973.392     2023782.347      184923.768
     2024044.871      184792.5062024120.96395736 184743.52669423
#Sta/Elev= 30
       0 1625.15    13.8 1615.33      37  1600.3      64 1586.25    79.5 1579.45
      87 1577.43   113.2 1576.14   135.2  1577.2   171.9 1577.81   197.6 1575.96
   223.3  1577.7   245.3 1577.26   252.6 1575.64   265.3 1576.82   275.1 1576.41
   281.9 1576.97   292.2 1575.55   304.3 1574.91   309.3  1573.8   319.1 1572.86
   326.5  1573.3   330.81574.927   333.3  1577.1   344.3 1590.24   351.6 1599.16
   355.3 1601.23   385.2 1611.29   407.9 1620.28   446.9 1639.56   478.2 1656.97
#Mann= 5 ,-1 , 0
       0      .1       0   135.2     .04       0   304.3    .045       0
   330.8     .04       0   344.3      .1       0
#XS Ineff= 2 , 0
          171.48  1578.7
Permanent Ineff=
       F       F
Bank Sta=304.3,330.8
XS Rating Curve= 0 ,0
Exp/Cntr=0.3,0.1

Type RM Length L Ch R = 1 ,3571    ,159.2,159.4,158.8
XS GIS Cut Line= 4
      2023726.32      185130.266     2023966.434      185080.643
      2024168.13       185055.03     2024264.176      184982.996
#Sta/Elev= 30
       0 1652.38    10.9 1647.09    34.4 1632.78    64.5  1610.9   108.1 1580.66
   124.8 1573.09   134.9 1571.92     155 1571.72   188.5 1572.99   215.3 1571.81
   242.1 1572.51     262 1572.01   268.6  1570.7   288.4 1571.85   292.51570.619
   298.4 1567.82   308.3 1568.39   315.61570.546   321.5 1571.38   331.4 1570.58
   364.4 1573.31   407.5 1572.53   420.7 1571.34     434 1571.82   456.5 1579.57
   503.4 1589.36   520.7    1595   536.2 1602.11   557.3 1615.17   568.6 1623.05
#Mann= 4 ,-1 , 0
       0      .1       0     190     .04       0   292.5    .045       0
   315.6      .1       0
#XS Ineff= 2 , 0
           188.8 1574.15  365.23         1574.22
Permanent Ineff=
       F       F
Bank Sta=292.5,315.6
XS Rating Curve= 0 ,0
Exp/Cntr=0.3,0.1

Type RM Length L Ch R = 1 ,3412    ,192.5,177.7,145.8
XS GIS Cut Line= 4
     2023764.738      185258.327     2023961.632      185240.719
     2024219.354      185208.703     2024355.419       185117.46
#Sta/Elev= 30
       0 1638.55    11.7 1633.58    31.5 1621.91    41.4 1614.51    91.7 1580.63
   100.7 1576.05   113.8 1571.14   120.4 1570.17   150.1 1570.24     216 1568.13
   245.8 1569.44     259 1567.71   272.2 1567.99   274.91567.412   282.1 1565.38
   285.4 1565.28   298.7 1566.23     301 1567.45   305.3 1569.25   321.8 1569.26
     335 1570.27   358.2 1569.11     378 1569.93   417.7 1570.09   440.8 1575.72
     473 1576.65   508.3 1579.38   548.2 1583.64   571.9 1587.97   621.2 1603.46
#Mann= 7 ,-1 , 0
       0      .1       0     150     .04       0  247.68      .1       0
   274.9    .045       0     301      .1       0  347.68    .035       0
  447.68      .1       0
#XS Ineff= 2 , 0
           183.3 1571.27  338.06         1571.27
Permanent Ineff=
       F       F
Bank Sta=274.9,301
XS Rating Curve= 0 ,0
Exp/Cntr=0.5,0.3

Type RM Length L Ch R = 1 ,3234    ,23.5,21.4,21
XS GIS Cut Line= 4
2023836.86026746185466.481076656     2024010.682      185434.551
     2024099.366      185367.573     2024363.231      185151.619
#Sta/Elev= 30
       0 1601.27    18.6  1591.5    38.6 1582.55    55.3 1578.05    78.6  1575.5
      82 1574.48    88.6 1570.84   108.7 1570.58   131.1 1567.34   151.6 1566.22
   183.3 1565.26   216.2 1566.09   220.3 1565.57   226.1 1563.54   232.6 1562.66
   240.2  1563.5   249.5 1564.63   287.9 1566.12   331.3 1569.26   345.4 1570.88
   383.5 1573.22   412.9 1573.39   438.6  1574.4   493.7  1578.1   506.5 1578.48
   517.8 1579.89     568 1583.66   583.1 1585.79   612.5 1596.31   628.8 1599.96
#Mann= 5 ,-1 , 0
       0    .035       0      80     .04       0   226.1    .045       0
   240.2     .04       0  427.86      .1       0
#XS Ineff= 2 , 0
             213 1565.84     260          1565.5
Permanent Ineff=
       F       F
#Block Obstruct= 2 ,-1
  183.66   203.61570.505  340.03  406.151576.191
Bank Sta=226.1,240.2
XS Rating Curve= 0 ,0
Exp/Cntr(USF)=0,0
Exp/Cntr=0.5,0.3

Type RM Length L Ch R = 3 ,3220    ,,,
BEGIN DESCRIPTION:
Merged Survey SLC030RP
Survey Point higher at the right abutment than at left causing the deck to look higher at right. Kept the center elevation of the survey and straightened the deck as the deck is straight in the image.
END DESCRIPTION:
Bridge Culvert--1,0,-1,-1, 0
Deck Dist Width WeirC Skew NumUp NumDn MinLoCord MaxHiCord MaxSubmerge Is_Ogee
4.7,6.5,2.6,0, 152, 51, , , 0.98, 0, 0,0,,
  159.09  162.43   171.3  172.46   175.8  179.15  182.49  193.88  197.89   201.9
  205.75  205.85  216.96  217.06   233.2  234.77  256.01  256.11   269.2  272.94
  273.04  274.52  279.19  281.52  284.19  292.59  295.53  300.98  304.47   307.2
  309.38  311.87  314.87  318.85  322.19  323.51  326.47  330.75  335.03  337.48
  340.41  343.59  344.47  347.87  350.63  352.15  355.74  356.43  360.77  364.99
  370.09  374.75   379.4  381.73  388.72  391.05  393.38  394.94  402.69  407.35
  411.95  414.34  417.06  420.62  429.18  433.46  437.49  442.02  446.94  449.27
  452.82  456.26  457.93   467.7  470.23  473.26  477.22  480.54  483.48  486.54
  488.59  493.38  495.85  497.66  498.18  500.51  501.93  503.92  505.17  506.21
  509.83  512.16  514.74  516.82  518.99  519.34  521.48  523.24   524.5   527.5
  529.65  531.75  533.13  536.01  540.12  542.45  544.78  547.11  549.44  550.26
  553.02  554.11  555.42  556.44  557.28  558.77  560.57  561.53  563.43  565.79
  568.09  570.04  570.88  572.75   574.3  575.08  577.41  579.74  581.18   582.8
   584.4  586.34  586.73  589.06  591.31  593.72  595.57  596.05  598.38  600.72
  604.08  606.95  607.71   612.1   614.7  616.84  617.26  621.09  622.41  627.56
   629.6  631.18
 1565.76 1565.74 1565.61 1565.58 1565.39 1565.26 1565.22  1565.3 1565.42 1565.56
 1565.68 1565.62 1568.26 1568.26 1568.26 1568.26 1568.26 1568.26 1566.22 1565.38
 1565.14 1565.19 1565.43 1565.56 1565.67 1566.13 1566.31 1566.57 1566.81 1567.07
 1567.24  1567.4 1567.54 1567.88 1568.14 1568.26  1568.5  1568.9 1569.21 1569.54
 1569.97 1570.39 1570.48 1570.84  1571.1 1571.22 1571.44 1571.47  1571.5 1571.68
 1571.97 1572.26 1572.63  1572.8 1573.09 1573.22 1573.28  1573.3 1573.32 1573.37
 1573.41 1573.47 1573.48 1573.55  1573.9 1574.16 1574.28 1574.46 1574.63 1574.75
 1574.99 1575.15 1575.24 1575.83 1575.94 1576.12 1576.38 1576.62 1576.79 1577.02
 1577.15 1577.36 1577.53 1577.62 1577.67  1577.8 1577.85 1578.01 1578.12 1578.18
 1578.51 1578.69 1578.91 1579.12 1579.42 1579.46  1579.6 1579.76 1579.85 1580.11
 1580.23 1580.32 1580.42 1580.68 1580.93  1581.1 1581.34 1581.63  1582.1 1582.29
 1582.71 1582.83 1583.06 1583.15 1583.25 1583.32 1583.54 1583.64 1583.72    1584
 1584.01  1584.1 1584.12 1584.11 1584.16  1584.2 1584.44 1584.75 1585.07 1585.33
 1585.34 1585.41 1585.41 1585.52  1585.8 1586.43 1587.01 1587.19 1588.11  1589.1
 1590.58 1591.74 1592.02 1593.81 1594.73 1595.53 1595.67 1596.83 1597.21 1598.64
  1599.1 1599.41
                                                                                
                        1566.8641566.8641566.8641566.864
                                                                                
                                                                                
                                                                                
                                                                                
                                                                                
                                                                                
                                                                                
                                                                                
                                                                                
                                                                                
                                                                                
                                                                                
                                                                                
                
  195.28  199.29   203.3  207.15  207.25  218.36  218.46   234.6  236.17  257.41
  257.51   270.6  274.34  274.44  275.92  280.59  282.92  285.59  293.99  296.93
  302.38  305.87   308.6  310.78  313.27  316.27  320.25  323.59  324.91  327.87
  332.15  336.43  338.88  341.81  344.99  345.87  349.27  352.03  353.55  357.14
  357.83  362.17  366.39  371.49  376.15   380.8  383.13  390.12  392.45  394.78
  396.34
  1565.3 1565.42 1565.56 1565.68 1565.62 1568.26 1568.26 1568.26 1568.26 1568.26
 1568.26 1566.22 1565.38 1565.14 1565.19 1565.43 1565.56 1565.67 1566.13 1566.31
 1566.57 1566.81 1567.07 1567.24  1567.4 1567.54 1567.88 1568.14 1568.26  1568.5
  1568.9 1569.21 1569.54 1569.97 1570.39 1570.48 1570.84  1571.1 1571.22 1571.44
 1571.47  1571.5 1571.68 1571.97 1572.26 1572.63  1572.8 1573.09 1573.22 1573.28
  1573.3
                                                1566.8511566.8511566.8511566.851
                                                                                
                                                                                
                                                                                
                                                                                
        
BR Coef=-1 , 1 , 0 ,, 0 ,,,0.8,0,1.2,0,
WSPro=,,,, 1 ,,,, 0 ,,,, 0 ,,,,-1 ,-1 ,-1 , 0 , 0 , 0 , 0 , 0
BR U #Sta/Elev= 30
       0 1601.27    18.6  1591.5    38.6 1582.55    55.3 1578.05    78.6  1575.5
    81.1  1574.7    88.6 1570.84   108.7 1570.58   135.3 1566.98   183.3 1565.26
   212.1 1566.25   219.1 1565.78   223.8 1564.26   228.5 1562.93   232.6 1562.66
   244.9  1564.2     287 1566.06   331.3 1569.26   345.4 1570.88   383.5 1573.22
   412.9 1573.39   433.9 1574.24   493.7  1578.1   508.5 1578.61   517.8 1579.89
   540.4  1581.3   574.3 1584.34   585.4 1586.43   612.5 1596.31   628.8 1599.96
BR U #Mann= 5
       0    .035    81.1     .04   223.8     .04   244.9     .04   433.9      .1
BR D #Sta/Elev= 30
       0 1602.21    25.1 1587.88    38.4 1582.07    51.8 1577.84    68.5 1575.21
    71.3 1573.48    75.1 1571.84    95.2 1571.56   145.3 1565.82     182  1565.2
   214.3 1566.02   226.2 1565.23   230.8 1564.23     235  1562.7     242 1561.47
   247.3 1561.88   254.3 1563.56   268.7 1564.93   315.1 1567.63   365.9 1572.07
   387.7 1573.16   419.7 1573.54   460.4 1575.23   519.9 1578.69   534.8 1580.45
     563 1582.34   588.6 1584.85   596.2 1586.58   617.7 1595.25   630.1 1598.94
BR D #Mann= 5
       0    .035    71.3     .04   230.8     .04   254.3     .04   419.7      .1
BC Design=,, 0 ,, 0 ,,0,,,,
BC HTab HWMax=0
BC HTab TWMax=0
BC HTab MaxFlow=0
BC Use User HTab Curves=0
BC User HTab FreeFlow(D)= 0

Type RM Length L Ch R = 1 ,3212    ,60.7,95.3,114.8
XS GIS Cut Line= 4
2023843.64964503185485.091327235     2024027.171      185450.399
     2024114.075      185381.579     2024369.232      185168.447
#Sta/Elev= 30
       0 1602.21    25.1 1587.88    38.4 1582.07    51.8 1577.84    68.5 1575.21
    75.1 1571.84    95.2 1571.56   138.6 1566.35   148.6 1565.67     182  1565.2
   219.2 1565.78   228.5 1564.82     235  1562.7     242 1561.47   247.3 1561.88
   249.2 1562.61   256.1 1563.89   265.4  1564.7   315.1 1567.63   365.9 1572.07
   422.1 1573.56   460.4 1575.23   490.3 1577.54   519.9 1578.69   534.8 1580.45
     563 1582.34   592.1 1585.44   599.1 1587.65   617.7 1595.25   630.1 1598.94
#Mann= 5 ,-1 , 0
       0    .035       0      70     .04       0     235    .045       0
   249.2     .04       0  417.63      .1       0
#XS Ineff= 2 , 0
           214.5 1565.98   261.5         1565.14
Permanent Ineff=
       F       F
#Block Obstruct= 2 ,-1
   197.3   209.9 1570.59  350.52  416.641577.205
Bank Sta=235,249.2
XS Rating Curve= 0 ,0
Exp/Cntr(USF)=0,0
Exp/Cntr=0.5,0.3

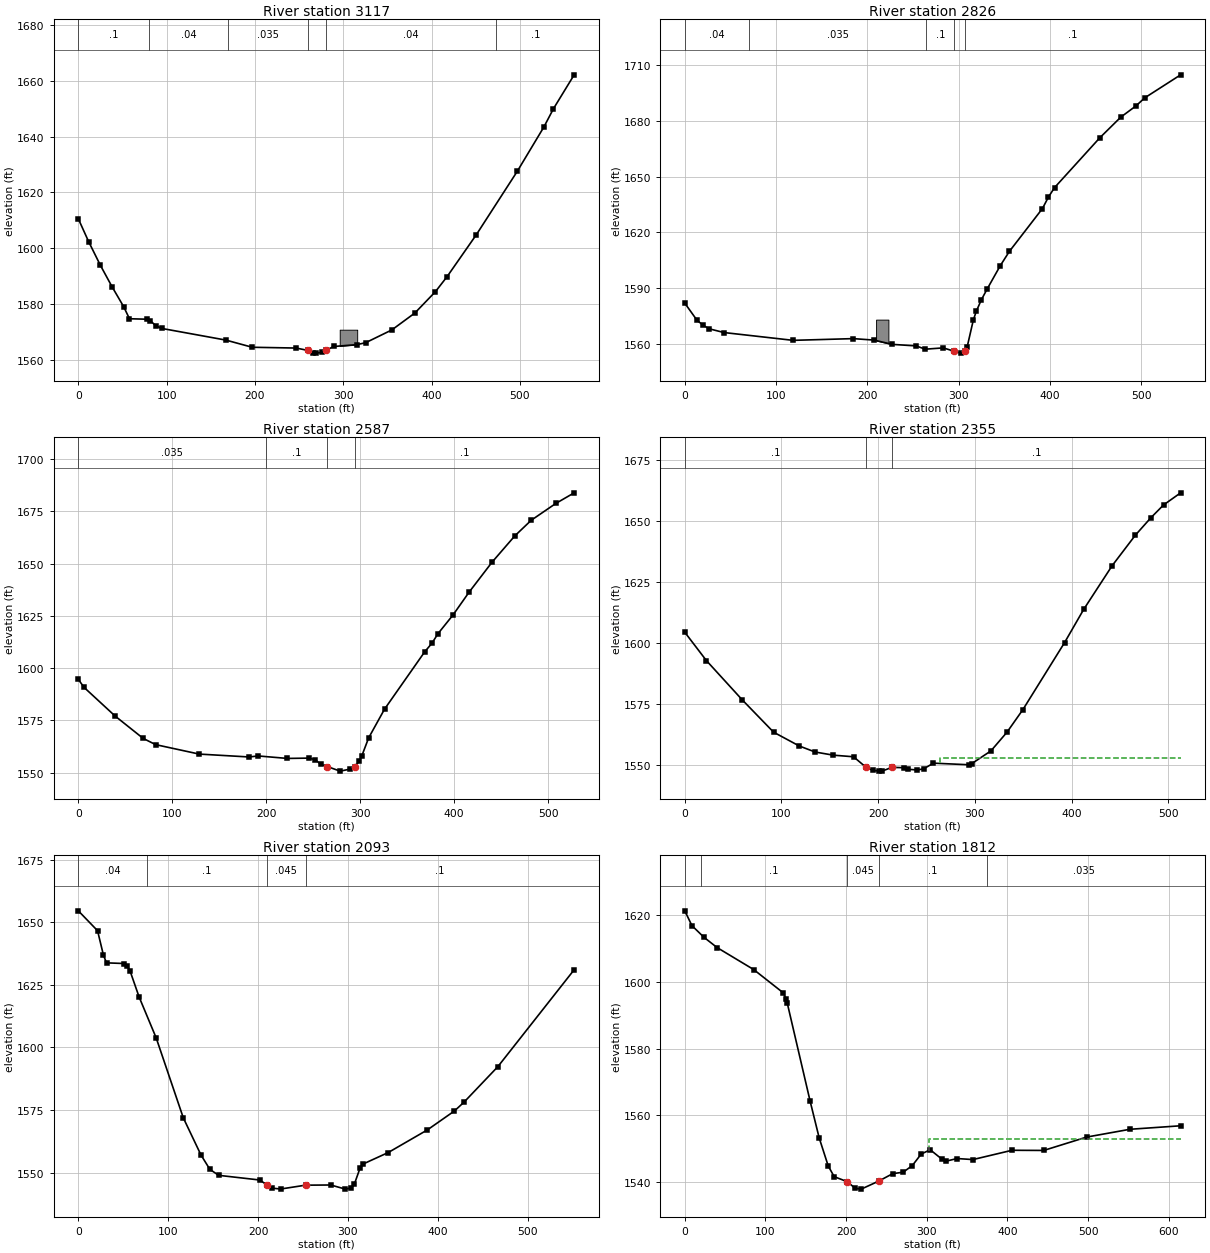
Type RM Length L Ch R = 1 ,3117    ,277.9,290.8,289.3
XS GIS Cut Line= 4
2023840.35123283185531.953662475      2024084.01       185499.83
     2024241.391      185490.472     2024398.177      185509.851
#Sta/Elev= 30
       0 1610.51    11.6 1602.38    24.9 1593.89    38.1 1586.21    51.3 1579.04
    57.9  1574.7    77.8 1574.53    81.3 1574.06    87.7  1572.2    94.3 1571.24
   167.1 1567.05   196.9 1564.48   246.6  1564.2   260.1 1563.34   266.2 1562.44
   269.4 1562.38   276.1 1562.68   280.21563.404   289.3 1564.76   315.6 1565.44
   325.3 1566.11     355  1570.7   381.1 1576.77   404.3  1584.4   417.5 1589.78
   450.6  1604.8   496.9 1627.49   527.2 1643.46     538 1649.99   561.4 1662.11
#Mann= 6 ,-1 , 0
       0      .1       0      80     .04       0     170    .035       0
   260.1    .045       0   280.2     .04       0  473.43      .1       0
#Block Obstruct= 1 ,-1
  295.95  315.74 1570.78
Bank Sta=260.1,280.2
XS Rating Curve= 0 ,0
Exp/Cntr(USF)=0,0
Exp/Cntr=0.3,0.1

Type RM Length L Ch R = 1 ,2826    ,233.6,239.3,240.8
XS GIS Cut Line= 4
 2023848.3204433185757.3518066552024062.60866771185772.503499291
 2024218.4546491185785.4906644072024389.45232313185804.971412081
#Sta/Elev= 30
       0 1581.81    13.4 1572.59      20 1569.95    26.6 1568.02      43 1565.99
   118.7 1561.79   184.5 1562.72   207.5 1561.92   227.2 1559.63   253.6 1558.79
   263.4 1557.03   283.2 1557.73  295.19 1555.93   302.9 1554.91   306.8 1555.96
   309.5 1558.46   316.1 1572.63   319.4 1577.45     325 1583.67   331.1 1589.24
   345.7 1602.01   355.6 1609.64   391.9 1632.76   398.5 1638.97   405.1 1643.99
   454.6 1670.77   477.7 1681.95   494.3 1687.98     504 1692.35   543.3 1704.74
#Mann= 5 ,-1 , 0
       0     .04       0      70    .035       0  264.82      .1       0
  295.19    .045       0   306.8      .1       0
#Block Obstruct= 1 ,-1
   209.6  223.09 1572.95
Bank Sta=295.19,306.8
XS Rating Curve= 0 ,0
Exp/Cntr(USF)=0,0
Exp/Cntr=0.3,0.1

Type RM Length L Ch R = 1 ,2587    ,228.7,232.5,215.3
XS GIS Cut Line= 4
2023819.53152276185969.292235739     2024035.919      185998.534
     2024181.766      186032.328     2024340.063      186051.892
#Sta/Elev= 30
       0 1594.63     6.1 1590.81    39.2 1577.09      69 1566.42    82.3 1563.44
   128.6 1558.93   181.6 1557.55   191.5 1558.03   222.5 1556.85     245    1557
   251.7  1556.3   258.4 1553.97   265.11552.928   278.6 1550.78   288.7  1551.7
   293.91552.922   298.8 1555.44   301.8 1558.24   308.9 1566.66   325.8 1580.39
   368.6 1607.84   376.2 1611.88   382.8 1616.55   398.8 1625.49   415.8 1636.34
   440.2 1650.65   464.4 1663.21   481.9  1670.7   508.1 1678.75   527.6 1683.82
#Mann= 4 ,-1 , 0
       0    .035       0     200      .1       0   265.1    .045       0
   293.9      .1       0
Bank Sta=265.1,293.9
XS Rating Curve= 0 ,0
Exp/Cntr(USF)=0,0
Exp/Cntr=0.3,0.1

Type RM Length L Ch R = 1 ,2355    ,262.3,261.4,254.3
XS GIS Cut Line= 2
2023800.08647552186192.7703480952024309.05503542186255.610287253
#Sta/Elev= 30
       0 1604.43    22.4 1592.78    59.4  1576.7    91.8 1563.44   118.3 1557.78
   134.8 1555.29   153.6    1554   174.5 1553.34   187.7 1548.94   194.3 1547.81
   200.9 1547.45   204.2 1547.49   214.2    1549   227.1 1548.85   230.7 1548.21
   240.6 1547.92   247.2 1548.43   257.1 1550.72   293.5 1550.07   296.8 1550.54
   316.6 1555.75   333.2 1563.41   349.7 1572.71   392.7 1600.14   412.5 1613.78
   441.9  1631.7     466 1644.27   481.9 1651.36   495.1 1656.65   512.8 1661.64
#Mann= 3 ,-1 , 0
       0      .1       0   187.7    .045       0   214.2      .1       0
#XS Ineff= 2 , 0
                           263.7            1553
Permanent Ineff=
       F       F
Bank Sta=187.7,214.2
XS Rating Curve= 0 ,0
Exp/Cntr(USF)=0,0
Exp/Cntr=0.3,0.1

Type RM Length L Ch R = 1 ,2093    ,265.4,281.2,297.8
XS GIS Cut Line= 4
2023745.57510501 186460.64057816     2023780.831      186467.356
     2024133.248      186479.4052024291.51617848186438.662742986
#Sta/Elev= 30
       0 1654.52    21.4 1646.58      28 1636.74    31.4 1633.75    51.2 1633.48
    54.4 1632.65    57.7 1630.38    67.6 1620.17    86.7 1603.74   116.8  1571.9
   136.5 1557.05   146.4 1551.31   156.2 1548.92   202.2 1547.04   210.21544.958
   215.3 1543.82   225.1 1543.45   252.9 1544.99     281 1545.06   297.3 1543.41
   303.9 1543.92   307.2 1545.37   313.8 1552.02   317.1 1553.46     345 1558.03
   388.5 1567.05   418.7 1574.63   429.5  1578.2     467 1592.32   551.9    1631
#Mann= 4 ,-1 , 0
       0     .04       0   75.89      .1       0   210.2    .045       0
   252.9      .1       0
Bank Sta=210.2,252.9
XS Rating Curve= 0 ,0
Exp/Cntr(USF)=0,0
Exp/Cntr=0.3,0.1

Type RM Length L Ch R = 1 ,1812    ,106.7,122.9,130.9
XS GIS Cut Line= 4
2023699.60461983186608.161335121     2023777.819      186678.204
     2024048.909      186822.7862024241.67007704186760.877397704
#Sta/Elev= 30
       0 1621.32     8.8 1616.89    23.7 1613.39      40  1610.3    85.5 1603.68
     122 1596.72   125.7 1594.85   126.9 1593.76   155.4 1564.17   166.6 1553.18
   177.8 1544.76   185.2 1541.54   201.61540.017   211.2 1538.04   218.7  1537.8
   240.6 1540.23   257.8 1542.45   270.7 1542.87   282.1 1544.88     293 1548.31
   304.2 1549.62   319.1 1546.73   324.2 1546.21   337.6 1546.98   357.2 1546.67
   405.7 1549.46     445 1549.41   498.2 1553.42   551.9 1555.76   614.7 1556.81
#Mann= 5 ,-1 , 0
       0     .04       0      20      .1       0   201.6    .045       0
   240.6      .1       0  374.99    .035       0
#XS Ineff= 2 , 0
                          302.25         1552.75
Permanent Ineff=
       F       F
Bank Sta=201.6,240.6
XS Rating Curve= 0 ,0
Exp/Cntr(USF)=0,0
Exp/Cntr=0.3,0.1

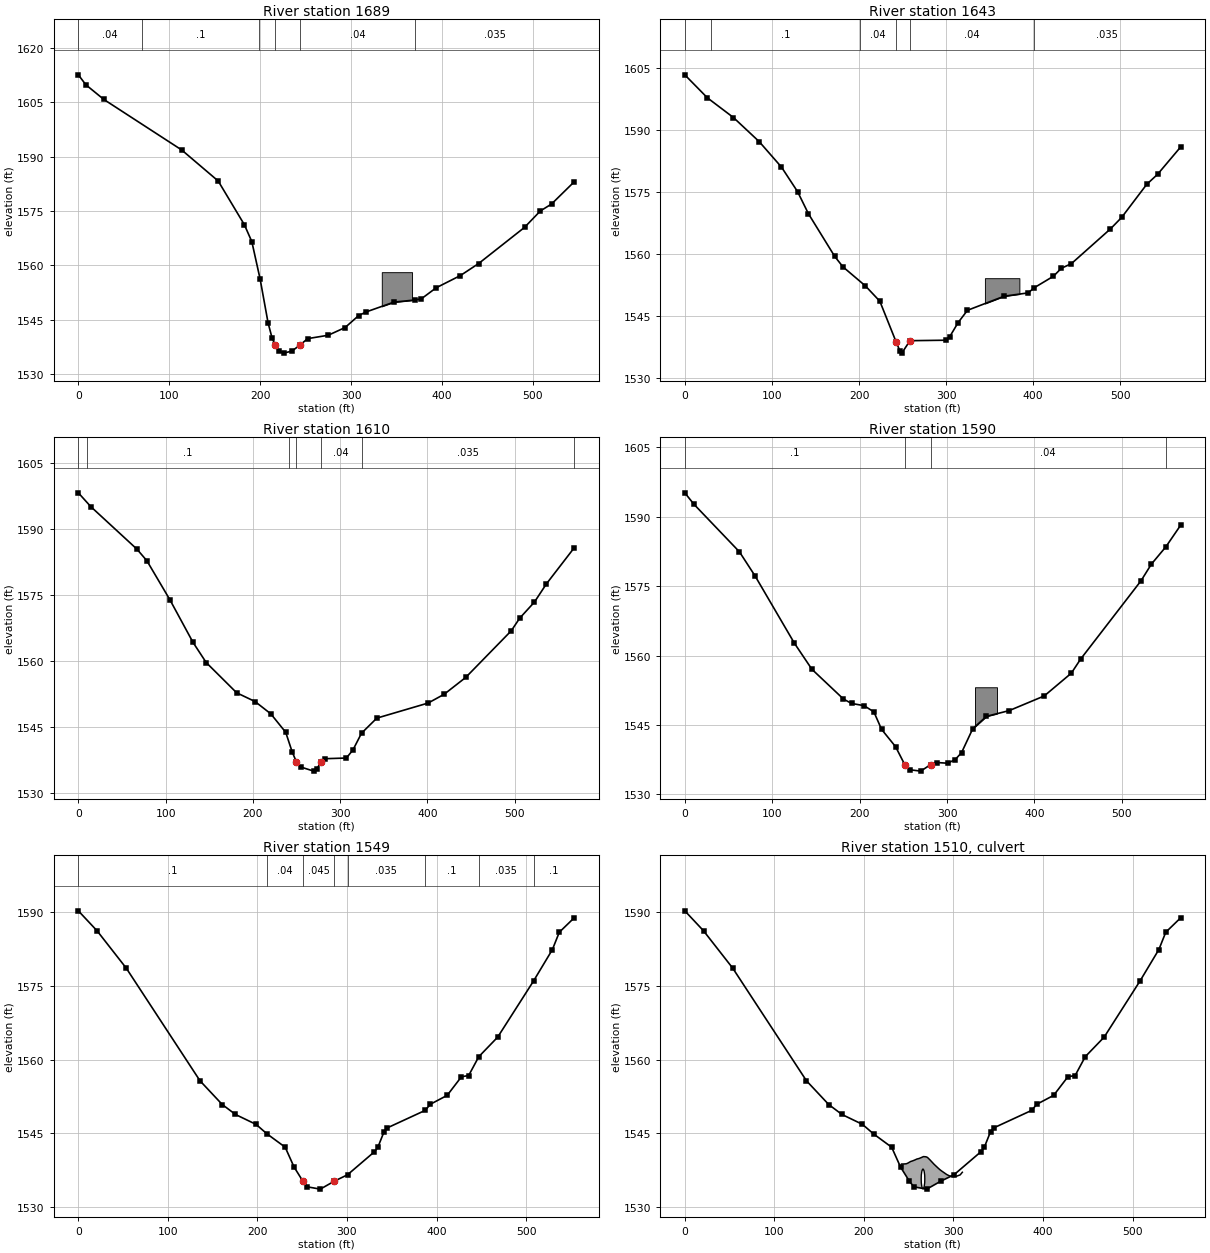
Type RM Length L Ch R = 1 ,1689    ,52.4,45.8,31.4
XS GIS Cut Line= 4
2023639.78557546186632.281600903     2023749.125      186761.455
      2023824.72      186848.197 2023990.2622142187049.996279957
#Sta/Elev= 30
       0 1612.57     8.3 1609.82    28.1 1605.77   113.7 1591.84   153.8 1583.29
   182.6 1571.23   190.8 1566.57     200 1556.15   208.7 1544.13   213.1 1539.96
   216.71537.932   220.7 1536.29   225.7 1535.81   234.8 1536.36   243.61538.006
   252.2 1539.81   274.8 1540.74   293.4 1542.87   308.2 1546.15   316.7 1547.19
     347 1549.87   370.3 1550.47   377.3  1550.8   393.6 1553.84   420.2 1557.21
   440.3 1560.53   490.7 1570.49   508.1 1575.02   520.4 1576.93   545.3 1583.05
#Mann= 6 ,-1 , 0
       0     .04       0      70      .1       0  199.24     .04       0
   216.7    .045       0   243.6     .04       0   370.3    .035       0
#Block Obstruct= 1 ,-1
  333.73  367.02 1558.14
Bank Sta=216.7,243.6
XS Rating Curve= 0 ,0
Exp/Cntr(USF)=0,0
Exp/Cntr=0.3,0.1

Type RM Length L Ch R = 1 ,1643    ,33.4,33.4,32.3
XS GIS Cut Line= 4
2023601.79352706186661.885002544     2023698.368      186815.661
     2023837.757      186877.9122023979.93090258187064.921229582
#Sta/Elev= 30
       0 1603.28      26 1597.71    55.9 1592.95    85.4 1587.14     111 1580.98
   129.5 1575.04   141.9 1569.72   172.1  1559.4   181.6 1556.87   207.3 1552.28
   223.9 1548.57   242.41538.836     247 1536.53   249.1 1536.03   258.51539.035
   299.4 1539.15   304.1 1539.99   313.8 1543.42   324.5 1546.38   366.7 1549.79
   394.3 1550.59   400.9  1551.8   423.2 1554.61   432.3 1556.54   443.8 1557.65
   488.5 1566.02   501.5 1568.82   530.3 1576.82   542.7 1579.23   569.2 1585.84
#Mann= 6 ,-1 , 0
       0     .04       0      30      .1       0  201.59     .04       0
   242.4    .045       0   258.5     .04       0   400.9    .035       0
#Block Obstruct= 1 ,-1
  344.53  384.11 1554.14
Bank Sta=242.4,258.5
XS Rating Curve= 0 ,0
Exp/Cntr(USF)=0,0
Exp/Cntr=0.3,0.1

Type RM Length L Ch R = 1 ,1610    ,19.7,19.4,19.1
XS GIS Cut Line= 4
2023575.89563234186677.118745136     2023665.889      186834.607
     2023817.458      186900.9182023951.23434151187077.111426306
#Sta/Elev= 30
       0 1598.27    14.3 1595.13    67.1 1585.47    78.5 1582.84     105 1573.93
   131.4 1564.27   146.5 1559.69   181.4 1552.81   202.5 1550.82   220.5 1548.03
   237.6 1543.83     245 1539.38   249.8 1537.13   254.8 1535.94   269.7    1535
   273.4 1535.49   277.7 1537.05   282.2 1537.82   307.1 1537.98   314.6  1539.8
   324.5 1543.63     342 1547.05   400.8 1550.48   419.2 1552.48   443.9 1556.31
     496  1566.9   505.7 1569.77   522.6 1573.44   536.3 1577.57   568.1 1585.76
#Mann= 7 ,-1 , 0
       0     .04       0      10      .1       0  241.39     .04       0
   249.8    .045       0   277.7     .04       0   324.5    .035       0
  568.05      .1       0
Bank Sta=249.8,277.7
XS Rating Curve= 0 ,0
Exp/Cntr(USF)=0,0
Exp/Cntr=0.3,0.1

Type RM Length L Ch R = 1 ,1590    ,43.2,41,40.2
XS GIS Cut Line= 4
2023560.57509695186687.560838314      2023649.65      186845.433
     2023794.452      186910.3912023923.28186962187097.527769324
#Sta/Elev= 30
       0 1595.19    10.5 1592.71    62.5 1582.43    80.4 1577.21   125.4 1562.66
   145.4 1557.03   181.5 1550.59   190.7 1549.64   205.1 1549.16   216.3 1547.81
   225.1 1544.03   241.1 1540.29   251.71536.374   257.2  1535.3   269.9    1535
   281.21536.408   288.3 1536.86   300.7 1536.71   309.4 1537.51   316.6    1539
   329.4 1544.17   345.1 1546.85   371.1 1548.09   411.2 1551.26   442.2 1556.19
   452.8 1559.23   521.9 1576.17   533.8 1579.78   550.3 1583.51   567.2 1588.18
#Mann= 4 ,-1 , 0
       0      .1       0   251.7    .045       0   281.2     .04       0
   550.3      .1       0
#Block Obstruct= 1 ,-1
  331.93  357.121553.139
Bank Sta=251.7,281.2
XS Rating Curve= 0 ,0
Exp/Cntr(USF)=0,0
Exp/Cntr=0.5,0.3

Type RM Length L Ch R = 1 ,1549    ,62.8,61.5,62.4
XS GIS Cut Line= 4
2023533.20940649186704.394577553     2023620.781      186872.681
     2023736.626      186924.0382023875.63573048187116.291776229
#Sta/Elev= 30
       0 1590.29    20.9 1586.23    53.5 1578.63   135.9  1555.7   160.7 1550.88
   175.5 1548.85   198.4 1546.84   210.8 1544.89     231 1542.19   240.9 1538.16
   250.9 1535.24   255.9 1534.12   270.2 1533.66   285.7 1535.26   300.6 1536.58
   330.7 1541.27   334.4 1542.14   341.4 1545.34   345.1 1546.13   387.3 1549.68
   393.1 1550.93   411.9 1552.74   427.8 1556.52   435.9 1556.78   447.2 1560.61
   468.3 1564.59   508.3    1576   529.4 1582.41   537.1 1585.93   553.7 1588.86
#Mann= 8 ,-1 , 0
       0      .1       0   210.8     .04       0   250.9    .045       0
   285.7     .04       0   300.6    .035       0   387.3      .1       0
   447.2    .035       0   508.3      .1       0
#XS Ineff= 2 , 0
       0     230  1538.5     306       0 1536.22
Permanent Ineff=
       F       F
Bank Sta=250.9,285.7
XS Rating Curve= 0 ,0
Exp/Cntr(USF)=0,0
Exp/Cntr=0.5,0.3

Type RM Length L Ch R = 2 ,1510    ,,,
BEGIN DESCRIPTION:
Walter Mann Rd/ Wright Rd
Culvert size assumed 4 ft
Deck from lidar
END DESCRIPTION:
Bridge Culvert--1,0,-1,-1, 0
Deck Dist Width WeirC Skew NumUp NumDn MinLoCord MaxHiCord MaxSubmerge Is_Ogee
24,12,2.6,0, 27, 27, , , 0.98, 0, 0,0,,
  242.07  244.51  246.94  247.97  249.37  252.04  254.23  256.66  259.13  261.53
  263.96  266.48  268.81  270.22  271.23  273.95  278.48  283.32  285.15  286.84
  292.61  295.42  297.84  300.59  303.81  307.52  309.94
 1538.77 1538.78 1538.81 1538.86 1538.98 1539.27  1539.4 1539.57 1539.78 1539.89
 1540.07 1540.28 1540.25 1540.19 1540.07 1539.58  1538.7 1537.87 1537.58 1537.35
 1536.62 1536.37 1536.26 1536.22 1536.31 1536.56 1537.09
                                                                                
                                                                                
                                                        
  245.07  247.51  249.94  250.97  252.37  255.04  257.23  259.66  262.13  264.53
  266.96  269.48  271.81  273.22  274.23  276.95  281.48  286.32  288.15  289.84
  295.61  298.42  300.84  303.59  306.81  310.52  320.94
 1538.77 1538.78 1538.81 1538.86 1538.98 1539.27  1539.4 1539.57 1539.78 1539.89
 1540.07 1540.28 1540.25 1540.19 1540.07 1539.58  1538.7 1537.87 1537.58 1537.35
 1536.62 1536.37 1536.26 1536.22 1536.31 1536.56 1537.09
                                                                                
                                                                                
                                                        
BR Coef=-1 , 1 , 0 ,, 0 ,,,0.8,0,1.2,0,
WSPro=,,,, 1 ,,,, 0 ,,,, 0 ,,,,-1 ,-1 ,-1 , 0 , 0 , 0 , 0 , 0
Culvert=1,4,,36,0.016,0.9,1,1,3,1533.73,266,1533.91,269,Culvert #1  , 0 ,24
     266     269
BC Culvert Barrel=1,Barrel #1,0
Culvert Bottom n=0.016
BC Design=,, 0 ,, 0 ,,,,,,
BC Use User HTab Curves=0
BC User HTab FreeFlow(D)= 0