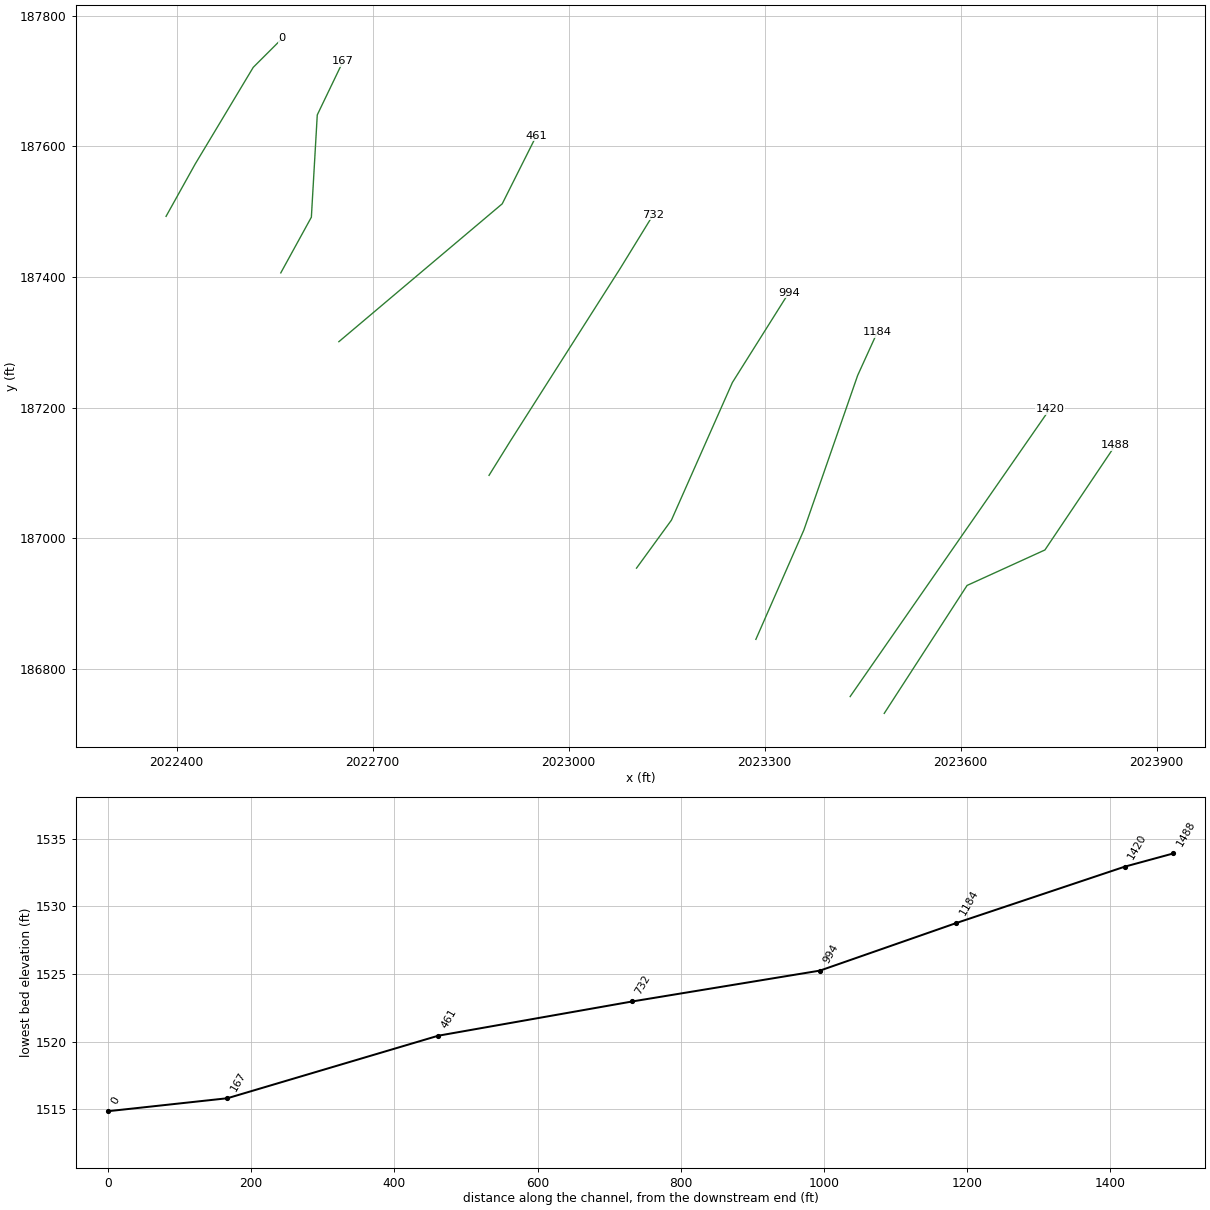
HEC-RAS study STNKLKCK_AE.prj: STNKLKCK_AE

--- STNKLKCK_AE.g01 (geometry) --- (continued)

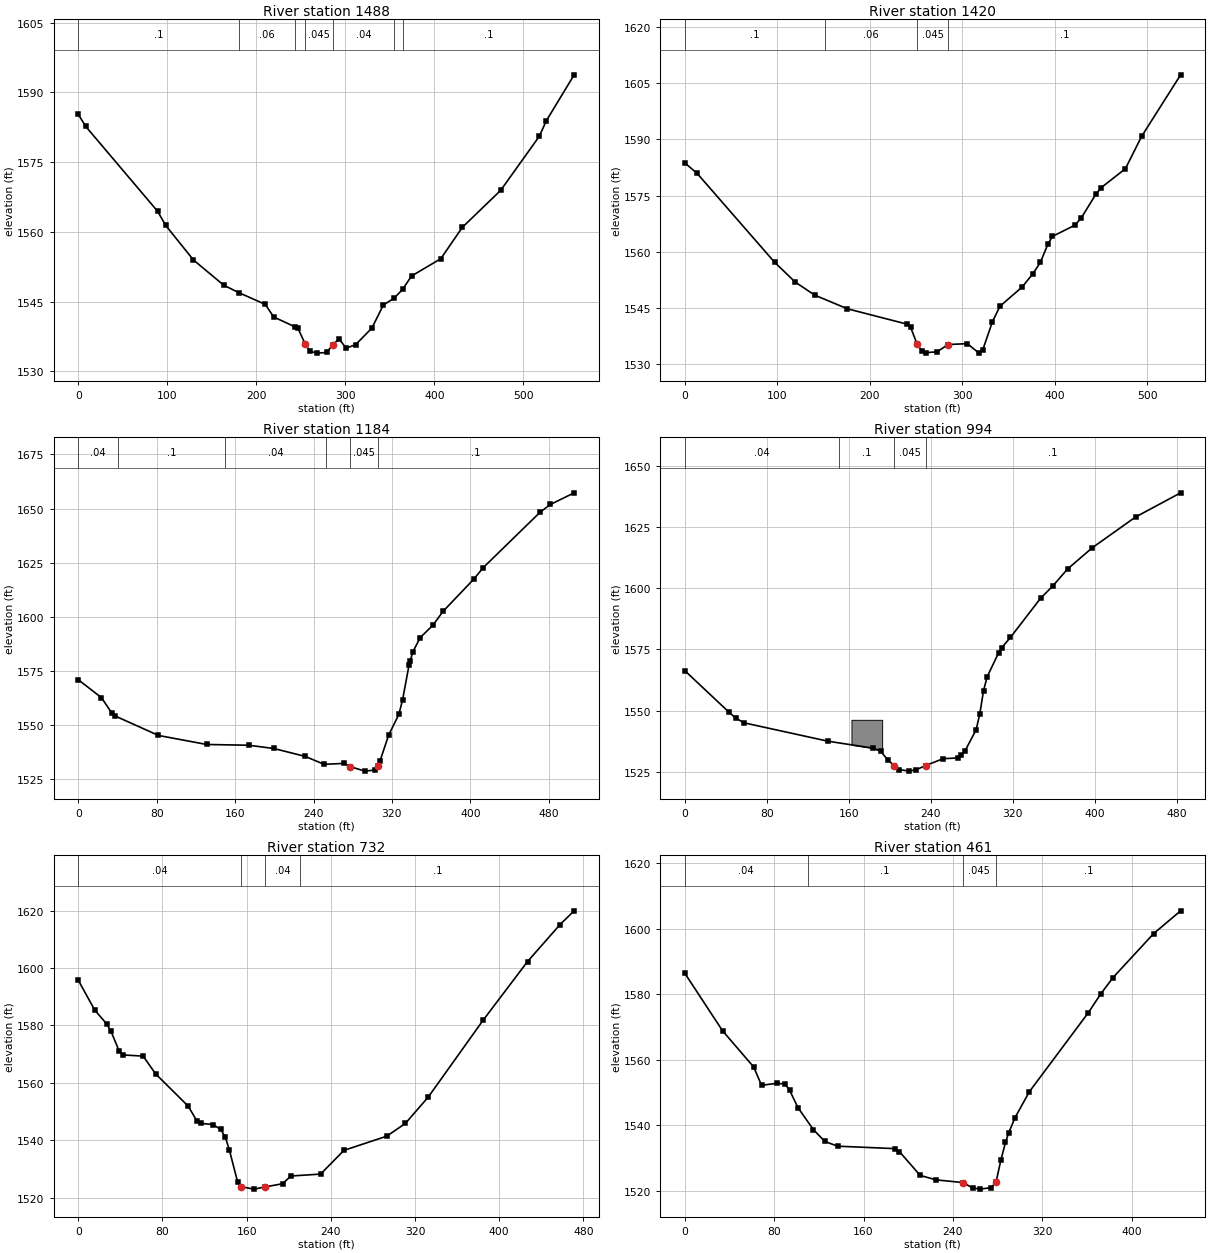
Type RM Length L Ch R = 1 ,1488    ,58.1,68,86.1
XS GIS Cut Line= 4
2023483.12589783186731.742790786     2023609.953      186927.633
     2023729.105      186981.9432023836.62830618187141.958454587
#Sta/Elev= 30
       0 1585.27     8.3 1582.68      89 1564.44    98.2 1561.37   129.3 1553.96
   163.3 1548.53   180.3 1546.92     210  1544.4   219.5 1541.69   243.7 1539.54
   246.8 1539.24   254.91535.863   260.4  1534.3   268.3 1533.91   279.3 1534.05
   285.71535.736   293.2 1536.93   300.9 1534.96   311.7 1535.76   329.8 1539.29
   342.7 1544.26   354.7 1545.71   364.3 1547.62   374.4  1550.5   407.3 1554.23
   431.5 1560.98   474.5 1568.92   517.9 1580.54   525.8 1583.89   557.1 1593.78
#Mann= 7 ,-1 , 0
       0      .1       0   180.3     .06       0   243.7     .04       0
   254.9    .045       0   285.7     .04       0   354.7    .035       0
   364.3      .1       0
#XS Ineff= 2 , 0
       0     249 1535.98   291.7       0 1535.87
Permanent Ineff=
       F       F
Bank Sta=254.9,285.7
XS Rating Curve= 0 ,0
Exp/Cntr(USF)=0,0
Exp/Cntr=0.5,0.3

Type RM Length L Ch R = 1 ,1420    ,226.3,235.5,240
XS GIS Cut Line= 3
2023430.95610632186757.488048877     2023431.982      186759.025
 2023736.7144976 187197.90494868
#Sta/Elev= 30
       0 1583.71    13.1 1580.98      97 1557.21   119.2 1551.94   140.4 1548.42
   175.8 1544.77   240.7 1540.64   244.2  1539.8   251.31535.247   256.7 1533.43
   260.6 1533.07   272.5 1533.26   284.71535.224   305.5 1535.46   318.1 1532.93
     322 1533.68   332.6  1541.3   340.8 1545.46   364.6 1550.55   376.2 1554.08
   384.5 1557.17   392.5 1561.96   397.4 1564.08   421.7 1567.08   428.5 1568.96
   444.4 1575.33   450.4 1577.14   476.4 1582.17     494 1590.83   536.1 1607.23
#Mann= 4 ,-1 , 0
       0      .1       0  151.85     .06       0   251.3    .045       0
   284.7      .1       0
Bank Sta=251.3,284.7
XS Rating Curve= 0 ,0
Exp/Cntr(USF)=0,0
Exp/Cntr=0.3,0.1

Type RM Length L Ch R = 1 ,1184    ,188.7,190.1,185.1
XS GIS Cut Line= 4
2023286.62429617186845.105635253     2023360.091      187012.488
     2023442.428      187249.1912023472.49770602187315.259687899
#Sta/Elev= 30
       0 1570.95    23.6 1562.69    34.3 1555.48    37.9 1554.15    81.8 1545.23
     131 1541.07     174 1540.71   199.4 1539.22   231.7 1535.54   250.7  1531.9
   271.6 1532.34   277.31530.865   292.4 1528.76   302.5 1529.26   305.41530.902
   307.7 1533.24   316.7 1545.41   327.1 1554.95   330.9  1561.7   337.6 1577.98
   338.6 1579.61   341.5 1583.95   348.9 1590.41   361.9 1596.17   372.3 1602.58
   403.6 1617.42   413.3 1622.77   471.4 1648.38   481.7 1651.88     506 1657.27
#Mann= 6 ,-1 , 0
       0     .04       0      40      .1       0     150     .04       0
   252.8      .1       0   277.3    .045       0   305.4      .1       0
Bank Sta=277.3,305.4
XS Rating Curve= 0 ,0
Exp/Cntr(USF)=0,0
Exp/Cntr=0.3,0.1

Type RM Length L Ch R = 1 ,994     ,265.6,262.1,255.9
XS GIS Cut Line= 4
 2023103.8819784186954.128357678     2023157.323       187027.61
     2023250.699      187238.4582023337.23844012187376.069834807
#Sta/Elev= 30
       0 1566.34      43 1549.41    50.1 1546.82    58.2 1544.97   139.7 1537.49
     184 1534.63   191.1 1533.42   198.3 1529.77   204.4  1527.5   209.3 1525.88
   219.3 1525.25   226.1 1525.88     2351527.514   252.1 1530.34   266.7 1530.63
   270.1  1531.7   273.7 1533.65   284.4 1542.19     288 1548.76   291.6 1558.14
   295.2 1563.89   306.3 1573.61   309.5 1575.81   317.9 1579.95   347.3 1595.95
     359 1600.87   373.6  1607.9   397.7 1616.58     440 1629.18     484 1639.07
#Mann= 4 ,-1 , 0
       0     .04       0  150.86      .1       0   204.4    .045       0
     235      .1       0
#Block Obstruct= 1 ,-1
  162.67  192.65 1546.24
Bank Sta=204.4,235
XS Rating Curve= 0 ,0
Exp/Cntr(USF)=0,0
Exp/Cntr=0.3,0.1

Type RM Length L Ch R = 1 ,732     ,266.7,270.8,244.8
XS GIS Cut Line= 4
2022878.08644976187096.190022215      2022910.33      187148.094
     2023079.008       187413.162023129.30442017187494.998132657
#Sta/Elev= 30
       0  1595.7    15.6 1585.33    27.2 1580.42    31.1 1577.89    38.8 1571.08
    42.5 1569.71    61.6 1569.31    73.5 1563.11   104.4 1551.89   112.5 1546.86
   116.2 1545.88   128.1 1545.47   135.3 1543.75   139.7 1541.12   143.6 1536.53
   151.4  1525.5   154.3 1523.83     167 1522.97   177.1 1523.71   194.2 1524.85
     202 1527.54   230.3 1528.21   252.5 1536.48   293.2 1541.42   310.9 1545.88
   332.5 1554.99   384.6 1581.73     427 1602.26   457.8 1615.11   471.3 1619.92
#Mann= 4 ,-1 , 0
       0     .04       0   154.3    .045       0   177.1     .04       0
   211.1      .1       0
Bank Sta=154.3,177.1
XS Rating Curve= 0 ,0
Exp/Cntr(USF)=0,0
Exp/Cntr=0.3,0.1

Type RM Length L Ch R = 1 ,461     ,267.3,294.4,307
XS GIS Cut Line= 3
     2022648.225      187300.891     2022898.308      187511.992
2022950.60112018187616.287450877
#Sta/Elev= 30
       0  1586.4    33.8 1568.82    61.7 1557.74    68.7 1552.16    82.7 1552.79
    89.8 1552.54    93.9 1550.61   101.3 1545.34   115.2 1538.59   125.4    1535
   136.8 1533.56   188.4 1532.81   192.1 1531.92   210.7 1524.64   224.7 1523.28
   248.91522.452   257.6 1520.83   264.3 1520.44   274.2 1520.89   278.61522.525
   282.9 1529.21   287.1 1534.71   289.9 1537.59   295.7 1542.32   308.5 1550.22
   361.3 1574.36   372.4 1580.09   383.4 1585.09   419.8 1598.53   443.9 1605.47
#Mann= 4 ,-1 , 0
       0     .04       0     110      .1       0   248.9    .045       0
   278.6      .1       0
Bank Sta=248.9,278.6
XS Rating Curve= 0 ,0
Exp/Cntr=0.3,0.1

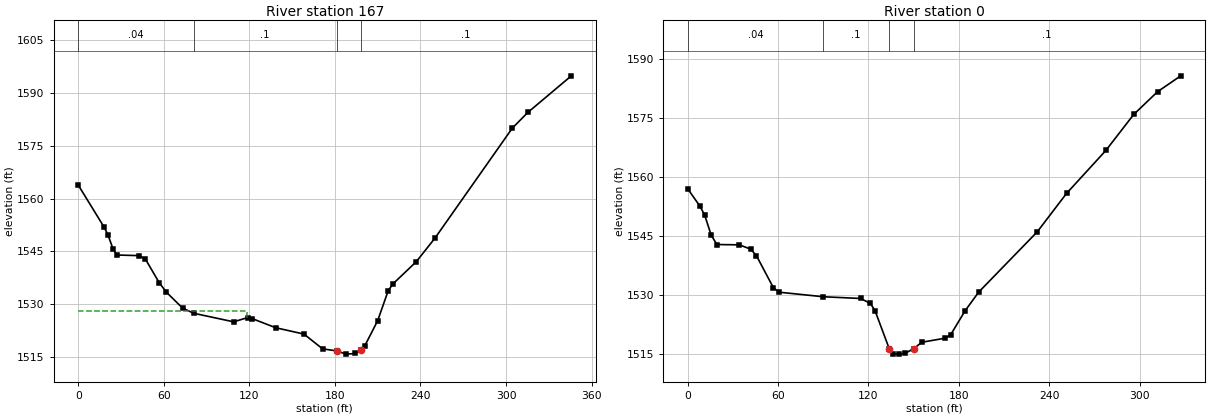
Type RM Length L Ch R = 1 ,167     ,189.7,167,158.8
XS GIS Cut Line= 4
2022559.29558317187406.212872013     2022606.106      187491.475
     2022615.142      187648.105 2022654.8391918187730.717574224
#Sta/Elev= 30
       0 1563.89    18.2 1551.89    20.8 1549.78    24.5 1545.66    27.1 1543.99
    42.3 1543.82      47 1542.92    56.8 1536.12    61.9  1533.4    73.2  1528.9
      81 1527.43     109    1525   118.8  1526.2   122.1  1525.9   138.5 1523.32
   158.3 1521.52   171.4 1517.31   181.3 1516.74   187.8 1515.82   194.4    1516
  198.31 1516.87     201 1518.21     210 1525.33   217.4 1533.86   220.7 1535.78
   237.1  1542.1   250.3 1548.86   304.5  1580.1   315.4 1584.55   345.8 1594.92
#Mann= 4 ,-1 , 0
       0     .04       0      81      .1       0   181.3    .045       0
  198.31      .1       0
#XS Ineff= 2 , 0
          118.61    1528
Permanent Ineff=
       F       F
Bank Sta=181.3,198.31
XS Rating Curve= 0 ,0
Exp/Cntr(USF)=0,0
Exp/Cntr=0.3,0.1

Type RM Length L Ch R = 1 ,0       ,204.8,191.6,171.7
XS GIS Cut Line= 4
 2022383.6551609 187492.78079626 2022427.9974868187572.451733917
2022517.13191059187720.935550034 2022561.6065498187765.350240692
#Sta/Elev= 30
       0 1556.94     8.1 1552.52    11.3 1550.23    15.6 1545.16    19.4 1542.73
    34.4 1542.65    41.9 1541.54    45.7 1539.86    56.9 1531.75    60.7 1530.61
      901529.452   114.8 1529.01   121.3 1527.75   124.4 1525.86  133.72 1516.29
   136.3 1514.95   140.5 1514.86   144.3 1515.05  149.98 1516.25   155.4 1517.88
   171.1 1518.93   174.6 1519.83   184.1 1525.88   193.1 1530.62     232 1545.97
   251.4 1555.72   277.5 1566.65     296 1575.81   311.8 1581.59   327.2 1585.63
#Mann= 4 ,-1 , 0
       0     .04       0      90      .1       0  133.72    .045       0
  149.98      .1       0
Bank Sta=133.72,149.98
XS Rating Curve= 0 ,0
Exp/Cntr=0.3,0.1
LCMann Table=0

Chan Stop Cuts=-1
Use User Specified Reach Order=0
Composite Channel Slope=5